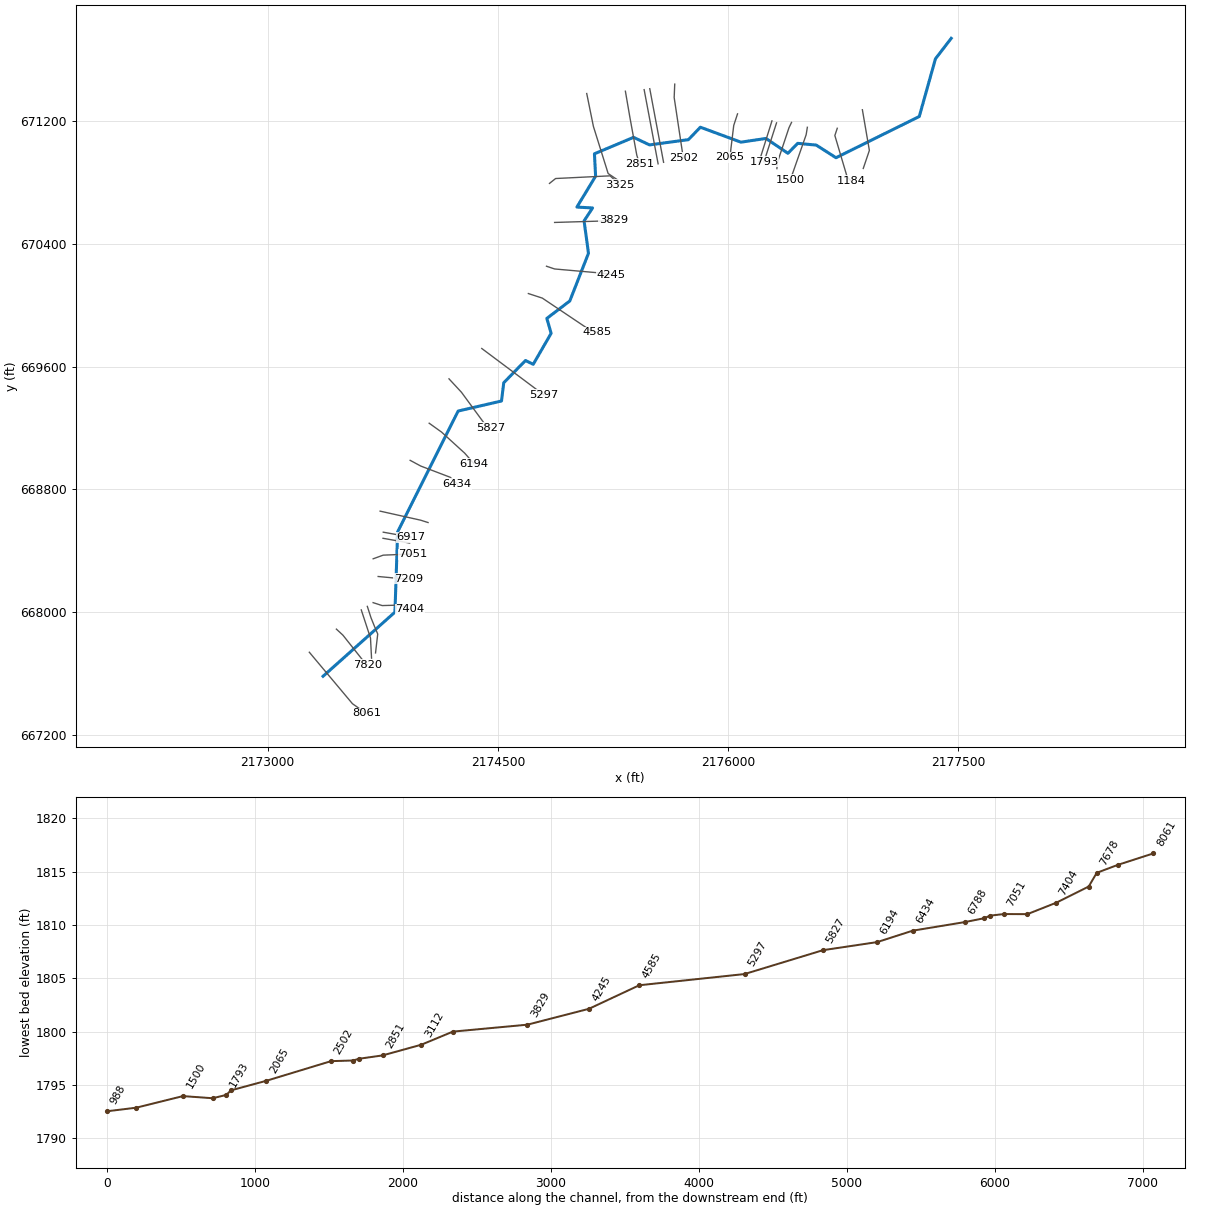
--- GRASSYCK.prj (project) ---

Proj Title=GRASSYCK
Current Plan=p01
Default Exp/Contr=0,0
English Units
Geom File=g01
Flow File=f01
Plan File=p01
BEGIN DESCRIPTION:
---------- MODELED AS PART OF WVEMD CTP PROGRAM, 2023----------
Stream Name: Grassy Creek
Flood Zone:  AFH
Upshur County, WV
HEC-RAS Version: RAS 6.3
Vertical Datum: NAVD88
Projection: NAD 1983 StatePlane West Virginia S FIPS 4702 (US Feet)
Terrain: 1-meter LIDAR (FEMA Region III 3DEP collected 2016-2018)
Land Use: 2019 NLCD
Hydrologic Method:
WV SIR2010-5033 regression equations
Additional Model Notes:
KWSE tie-in with Laurel Fork; 2 shared XS DS of confluence
END DESCRIPTION:
DSS Export Rating Curves= 0
DSS Export Rating Curve Sorted= 0
DSS Export Volume Flow Curves= 0
DXF OffsetX= 0
DXF OffsetY= 0
DXF ScaleX= 0
DXF ScaleY= 0

--- GRASSYCK.p01 (plan) ---

Plan Title=Floodplain
Program Version=6.30
Short Identifier=Floodplain
Geom File=g01
Flow File=f01
Subcritical Flow
K Sum by GR= 0
Std Step Tol= 0.01
Critical Tol= 0.01
Num of Std Step Trials= 20
Max Error Tol= 0.3
Flow Tol Ratio= 0.001
Split Flow NTrial= 30
Split Flow Tol= 0.02
Split Flow Ratio= 0.02
Log Output Level= 0
Friction Slope Method= 1
Unsteady Friction Slope Method= 2
Unsteady Bridges Friction Slope Method= 1
Parabolic Critical Depth
Global Vel Dist= 0 , 0 , 0
Global Log Level= 0
CheckData=False
Encroach Param=-1 ,0,0, 0
Mapping Interval=1HOUR
Computation Time Step Use Courant=        0
Computation Time Step Use Time Series=    0
Computation Time Step Count To Double=0
Computation Time Step Max Doubling=0
Computation Time Step Max Halving=0
Computation Time Step Residence Courant=0
Run HTab= 0
Run UNet= 0
Run Sediment= 0
Run PostProcess= 0
Run WQNet= 0
Run RASMapper=-1
UNET Theta= 0
UNET Theta Warmup= 0
UNET ZTol= 0
UNET ZSATol= 0
UNET MxIter= 0
UNET Max Iter WO Improvement= 0
UNET MaxInSteps= 0
UNET DtIC= 0
UNET DtMin= 0
UNET MaxCRTS= 0
UNET WFStab= 0
UNET SFStab= 0
UNET WFX= 1
UNET SFX= 1
UNET Gravity=32.17405
UNET 1D Methodology=Finite Difference
UNET DSS MLevel= 1
UNET Pardiso=0
UNET DZMax Abort= 0
UNET Use Existing IB Tables= 0
UNET Froude Reduction=False
UNET Froude Limit= 0
UNET Froude Power= 0
UNET D1 Cores= 0
UNET WindReference=Eulerian
UNET WindDragFormulation=Hsu (1988)
UNET D2 Coriolis=0
UNET D2 Cores= 0
UNET D2 Theta= 1
UNET D2 Theta Warmup= 1
UNET D2 Z Tol= 0.01
UNET D2 Volume Tol= 0.01
UNET D2 Max Iterations= 20
UNET D2 Equation= 0
UNET D2 RampUpFraction=0.1
UNET D2 TimeSlices= 1
UNET D2 Turbulence Formulation=Non-Conservative (original)
UNET D2 Eddy Viscosity=0.3
UNET D2 Transverse Eddy Viscosity=0.1
UNET D2 Smagorinsky Mixing=0
UNET D2 BCVolumeCheck=0
UNET D2 Cores=0
UNET D2 SolverType=PARDISO (Direct)
UNET D2 Minimum Iterations= 3
UNET D2 Maximum Iterations= 30
UNET D2 Restart Number= 10
UNET D2 Relaxation Coeff=1.3
UNET D2 SOR Precondition Iterations= 10
UNET D2 ILUT Maximum Fill= 8
UNET D2 ILUT Tolerance=1E-08
UNET D2 Convergence Tolerance=0.00001
UNET D1D2 MaxIter= 0
UNET D1D2 ZTol=0.01
UNET D1D2 QTol=0.1
UNET D1D2 MinQTol=1
Write IC File= 0
Write IC File at Fixed DateTime=0
Write IC File at Sim End=0
Echo Input=False
Echo Parameters=False
Echo Output=False
Write Detailed= 0
HDF Write Warmup=0
HDF Write Time Slices=0
HDF Flush=0
HDF Compression= 1
HDF Chunk Size= 1
HDF Spatial Parts= 1
HDF Use Max Rows=0
HDF Fixed Rows= 1
Calibration Method= 0
Calibration Iterations= 20
Calibration Max Change=0.05
Calibration Tolerance=0.2
Calibration Maximum=1.5
Calibration Minimum=0.5
Calibration Optimization Method= 1
WQ AD Non Conservative
WQ ULTIMATE=-1
WQ Max Comp Step=1HOUR
WQ Output Interval=15MIN
WQ Output Selected Increments= 0
WQ Output face flow=0
WQ Output face velocity=0
WQ Output face area=0
WQ Output face dispersion=0
WQ Output cell volume=0
WQ Output cell surface area=0
WQ Output cell continuity=0
WQ Output cumulative cell continuity=0
WQ Output face conc=0
WQ Output face dconc_dx=0
WQ Output face courant=0
WQ Output face peclet=0
WQ Output face adv mass=0
WQ Output face disp mass=0
WQ Output cell mass=0
WQ Output cell source sink temp=0
WQ Output nsm pathways=0
WQ Output nsm derived pathways=0
WQ Create Restart=0
WQ Fixed Restart=0
WQ System Summary=0
WQ Write To DSS=0
Sorting and Armoring Iterations= 10
XS Update Threshold= 0.02
Bed Roughness Predictor= 0
Hydraulics Update Threshold= 0.02
Energy Slope Method= 1
Volume Change Method= 1
Sediment Retention Method= 0
Sediment TS Multiplier= 1
Warm Up Method= 0
XS Weighting Method= 0
Number of US Weighted Cross Sections= 1
Number of DS Weighted Cross Sections= 1
Upstream XS Weight=0
Main XS Weight=1
Downstream XS Weight=0
Number of DS XS's Weighted with US Boundary= 1
Upstream Boundary Weight= 1
Weight of XSs Associated with US Boundary= 0
Number of US XS's Weighted with DS Boundary= 1
Downstream Boundary Weight= 0.5
Weight of XSs Associated with DS Boundary= 0.5
Percentile Method= 0
Sediment Output Level= 3
Mass or Volume Output= 0
Output Increment Type= 1
Profile and TS Output Increment= 1
Transport Output Increment 1
XS Output Flag= 0
XS Output Increment= 10
Read HDF5 Sediment Hotstart= 0
Sediment Hotstart Type= 0
Write Gradation File= 0
Read Gradation Hotstart= 0
Write HDF5 File= 1
Write Binary Output= 1
Write DSS Sediment File= 0
DSS Sediment Output Type= 1
SV Curve= 0
Specific Gage Flag= 0
Subcell Erosion Methods= 0
Subcell Deposition Methods= 0
Advection Scheme= 1
Matrix Solver= 0
Implicit Weighting Factor= 1
Maximum Outer Loop Convergence Iterations= 5
Convergence Maximum Absolute= 0.001
Convergence RMSE= 0.0001
Grain Fractions Max Abs Error= 0.001
Max Subgrid Regions= 1
Max Subgrid Length Scale= 3.402823E+38
Initial Layer Thickness= 3.402823E+38
Min Layer Thickness= 3.402823E+38
Max Layer Thickness= 3.402823E+38
Number of Layers= 5

--- GRASSYCK.f01 (steady flow) ---

Flow Title=Flows
Program Version=6.31
Number of Profiles= 1
Profile Names=01pct
River Rch & RM=GRASSYCK,Main,8061
     356
River Rch & RM=GRASSYCK,Main,3325
     563
Boundary for River Rch & Prof#=GRASSYCK,Main            , 1
Up Type= 0
Dn Type= 1
Dn Known WS=1775.68
DSS Import GetInterval= 0
DSS Import GetPeak= 0
DSS Import FillOption= 0

--- GRASSYCK.g01 (geometry) ---

Geom Title=Geometry
Program Version=6.31

River Reach=GRASSYCK        ,Main
Reach XY= 30
2173360.41678317 667581.897077592173828.84700002667999.891000003
2173846.58900002668523.5130000112174240.75099999669310.062999994
     2174523.052669375.4229999932174537.81800003 669494.43900001
2174679.32600002669639.2380000052174729.94800001669614.628000021
2174846.47400001669816.459000006     2174818.516669913.612000018
     2174968.237670027.2470000092175089.82799999670338.136000007
2175061.18300001670548.8100000022175116.52699998670633.228000015
     2175014.395670638.9229999932175136.21500002 670840.01000002
2175128.66100003670986.0680000042175383.71800004 671093.26500003
2175487.36700001671044.0160000032175740.93700001671078.269999996
2175818.88800001671159.2540000232176083.01700002671061.872999996
2176246.53100003671086.0250000062176389.24100001670989.245000005
2176453.19900003      671054.1472176574.07400003671042.671000019
2176702.47600003670960.4280000032177245.09999999671229.164000005
2177350.40800001671604.8690000182177453.02972811671738.328941718

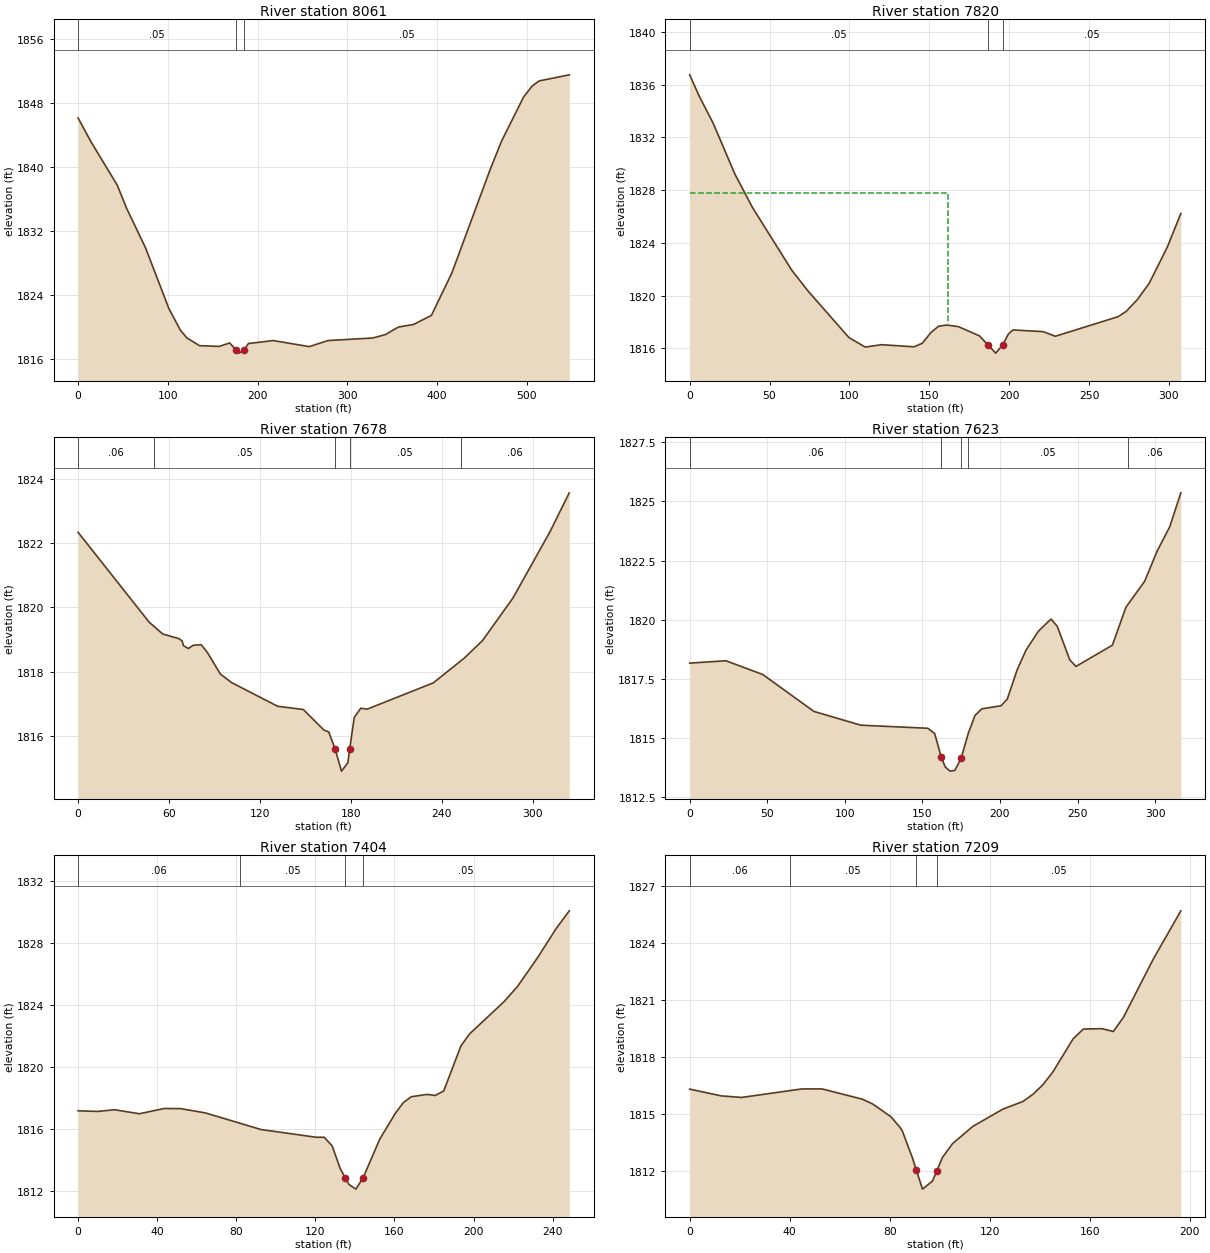
Type RM Length L Ch R = 1 ,8061    ,240.5,240.8,240.3
XS GIS Cut Line= 3
 2173271.0531462667738.639844911 2173552.1231841667403.205228937
2173642.01214945667340.282953193
#Sta/Elev= 30
       0 1846.09    14.2 1843.14    43.7 1837.68    54.1 1834.79      75 1829.91
   101.2 1822.28   113.9  1819.6   121.1 1818.63   135.3 1817.65   157.4 1817.56
   168.9 1817.99   176.1  1817.1   179.3 1816.72   184.6 1817.08   189.8 1817.92
   217.6 1818.29   257.6 1817.53   278.5 1818.29   328.4 1818.61   342.6 1819.04
   356.7 1819.97   373.8  1820.3   393.7 1821.43   416.4 1826.71   459.2 1839.66
   471.9  1843.2   496.3 1848.68     506 1850.08   513.8 1850.71   547.3 1851.47
#Mann= 3, -1 ,  0
       0    0.05       0   176.1   0.045       0   184.6    0.05       0
Bank Sta=176.1,184.6
XS Rating Curve= 0 ,0
Exp/Cntr(USF)=0,0
Exp/Cntr=0.3,0.1

Type RM Length L Ch R = 1 ,7820    ,145.3,141.7,138.4
XS GIS Cut Line= 4
2173447.41208185667889.2089219382173489.98991347667849.838803134
 2173631.2773997667671.6876028992173648.20906496 667657.43265179
#Sta/Elev= 30
       0 1836.75     5.9 1835.15    14.7 1833.08    28.3 1829.22    39.2 1826.71
    63.9 1821.93    74.1 1820.35    99.7 1816.82   109.9  1816.1   120.1 1816.28
   140.5 1816.12   145.6 1816.39   151.1 1817.21   155.8 1817.68   160.9 1817.77
   168.2 1817.65   181.4 1816.95   186.5 1816.29   191.6 1815.64     1961816.276
   199.5 1817.08   202.4  1817.4   221.3 1817.27   228.9 1816.92   268.1  1818.4
   273.3 1818.81   280.4 1819.72   287.8 1820.96   299.1  1823.7   307.5 1826.24
#Mann= 3, -1 ,  0
       0    0.05       0   186.5   0.045       0     196    0.05       0
#XS Ineff= 2 , 0
          161.54  1827.8
Permanent Ineff=
       T       F
Bank Sta=186.5,196
XS Rating Curve= 0 ,0
Exp/Cntr(USF)=0,0
Exp/Cntr=0.3,0.1

Type RM Length L Ch R = 1 ,7678    ,53.6,54.6,54.2
XS GIS Cut Line= 3
2173609.54935837668014.3234882122173669.59834207667831.491893602
2173676.46783489667700.043679526
#Sta/Elev= 29
       0 1822.34    46.9 1819.54    55.9 1819.17    66.4 1819.03    68.6 1818.96
    69.5 1818.81    72.8 1818.72    75.9 1818.82    81.2 1818.84    85.4 1818.59
    93.8 1817.93   101.2 1817.66   131.7 1816.92   148.6 1816.82   162.2 1816.18
   165.4 1816.12   169.6 1815.59   173.8  1814.9     178 1815.16  179.26  1815.6
   182.2 1816.57   186.5 1816.86   190.7 1816.83   234.4 1817.65   254.8 1818.42
   266.9 1818.97   286.9 1820.29   311.3 1822.35   324.1 1823.57
#Mann= 5, -1 ,  0
       0    0.06       0      50    0.05       0   169.6   0.045       0
  179.26    0.05       0  252.44    0.06       0
Bank Sta=169.6,179.26
XS Rating Curve= 0 ,0
Exp/Cntr(USF)=0,0
Exp/Cntr=0.3,0.1

Type RM Length L Ch R = 1 ,7623    ,207.8,219.8,231.6
XS GIS Cut Line= 5
2173649.03368899668037.3355236172173672.91902981667963.290967085
 2173696.0081926667905.9661491252173716.70882131667857.399289464
2173702.37761682667733.991695244
#Sta/Elev= 30
       0 1818.17    23.3 1818.27    47.1 1817.69    80.1 1816.13   110.3 1815.55
   153.5 1815.42   157.9  1815.2   162.2 1814.19   164.7 1813.79   167.8 1813.61
   170.9 1813.64     1751814.155   179.6 1815.21   183.9 1815.96   188.3 1816.24
   200.7 1816.37   204.7 1816.65   211.1 1817.89   216.8 1818.72   224.8 1819.52
   232.9 1820.03   236.9 1819.73     245 1818.31     249 1818.03   272.5 1818.93
   281.2 1820.53   293.3 1821.63   301.3  1822.9   309.4 1823.92   316.6 1825.36
#Mann= 5, -1 ,  0
       0    0.06       0   162.2   0.045       0     175    0.06       0
   179.6    0.05       0   282.4    0.06       0
Bank Sta=162.2,175
XS Rating Curve= 0 ,0
Exp/Cntr(USF)=0,0
Exp/Cntr=0.3,0.1

Type RM Length L Ch R = 1 ,7404    ,194.2,195.1,192.4
XS GIS Cut Line= 4
2173686.70613544668061.7388795122173745.62330945668042.630606858
2173864.25383551668045.8153189672173926.35572163668018.745266041
#Sta/Elev= 30
       0 1817.15      10 1817.11    18.4 1817.22      31 1816.96    43.6  1817.3
      52 1817.29    64.5 1817.01    92.5 1815.94   120.5 1815.44   124.5 1815.44
   128.5 1814.88   132.5 1813.44     1351812.838     137 1812.39   140.5 1812.09
   144.2 1812.84   152.6 1815.33   160.5    1817   164.5 1817.68   168.5 1818.06
   176.5 1818.21   180.6 1818.14   184.9 1818.43   193.6 1821.34     198 1822.12
   215.4  1824.2   222.2 1825.18   232.3 1827.03   241.8 1828.93   248.4 1830.07
#Mann= 4, -1 ,  0
       0    0.06       0   81.94    0.05       0     135   0.045       0
   144.2    0.05       0
Bank Sta=135,144.2
XS Rating Curve= 0 ,0
Exp/Cntr(USF)=0,0
Exp/Cntr=0.3,0.1

Type RM Length L Ch R = 1 ,7209    ,155.8,158.1,158.7
XS GIS Cut Line= 3
2173719.51237735668232.1209703842173894.35307213668215.640085221
2173915.13331864668216.356645445
#Sta/Elev= 30
       0  1816.3    12.7 1815.94    20.8 1815.86    44.9 1816.31    52.9 1816.31
      69 1815.77    73.1 1815.52    80.4 1814.85    84.1 1814.28      85  1814.1
    89.1 1812.66    90.6 1812.03    93.1 1811.02    97.1 1811.45    98.8 1811.98
   101.1  1812.7   105.1 1813.42   113.2 1814.33   125.2 1815.24   133.3 1815.65
   137.3 1816.03   141.3 1816.54   145.3 1817.22   153.3 1818.95   157.4 1819.47
   164.9 1819.49   169.4 1819.34   173.4 1820.08   185.4 1823.17   196.4 1825.71
#Mann= 4, -1 ,  0
       0    0.06       0      40    0.05       0    90.6   0.045       0
    98.8    0.05       0
Bank Sta=90.6,98.8
XS Rating Curve= 0 ,0
Exp/Cntr(USF)=0,0
Exp/Cntr=0.3,0.1

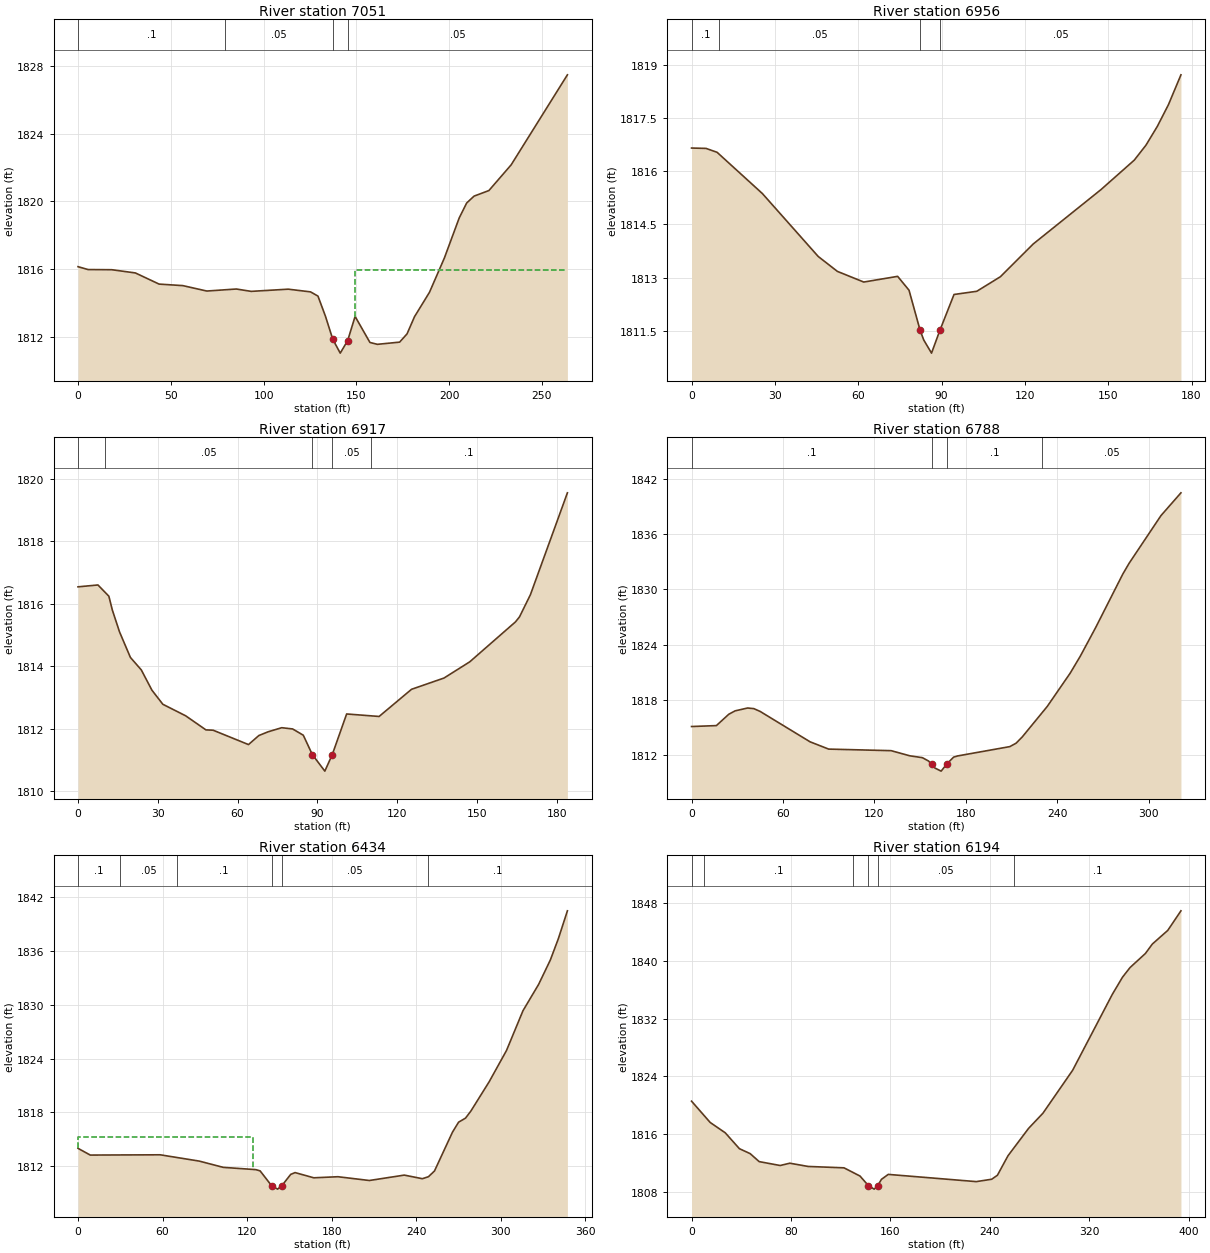
Type RM Length L Ch R = 1 ,7051    ,96,94.1,92.3
XS GIS Cut Line= 4
2173687.08111327668347.476609071 2173752.2880937668371.123096479
 2173889.8676568668376.8555782752173946.47591454  668377.5721385
#Sta/Elev= 30
       0 1816.14     5.4 1815.97    18.2 1815.96    30.9 1815.77    43.7 1815.11
    56.5 1815.02    69.4  1814.7    85.3 1814.82    93.3 1814.68   113.3 1814.81
   125.3 1814.65   129.3  1814.4   133.3 1813.22   137.3 1811.84   141.3 1811.03
   145.3 1811.77   149.3  1813.2   157.3 1811.66   161.3 1811.55   173.3 1811.68
   177.3 1812.17   181.3 1813.18   189.4 1814.63   197.4 1816.65   205.4 1819.02
   209.4  1819.9   213.4 1820.31   221.4 1820.64   233.4 1822.16   263.7 1827.48
#Mann= 4, -1 ,  0
       0     0.1       0   79.36    0.05       0   137.3   0.045       0
   145.3    0.05       0
#XS Ineff= 2 , 0
                          149.23         1815.96
Permanent Ineff=
       F       T
Bank Sta=137.3,145.3
XS Rating Curve= 0 ,0
Exp/Cntr(USF)=0,0
Exp/Cntr=0.3,0.1

Type RM Length L Ch R = 1 ,6956    ,39.3,39.3,39.3
XS GIS Cut Line= 2
2173751.10150196668481.0298640332173924.58137722668450.141983805
#Sta/Elev= 23
       0 1816.65     5.2 1816.64     9.2 1816.53    25.5 1815.37    45.6  1813.6
    52.5 1813.18      62 1812.88    74.2 1813.04    78.3 1812.65    82.3 1811.52
    83.6 1811.25    86.4 1810.88    89.41811.519    94.5 1812.53   102.7 1812.62
   111.2 1813.03     123 1813.95   147.4 1815.48   159.4 1816.31   163.6 1816.73
   167.7 1817.26   171.7 1817.87   176.2 1818.71
#Mann= 4, -1 ,  0
       0     0.1       0      10    0.05       0    82.3   0.045       0
    89.4    0.05       0
Bank Sta=82.3,89.4
XS Rating Curve= 0 ,0
Exp/Cntr(USF)=0,0
Exp/Cntr=0.3,0.1

Type RM Length L Ch R = 1 ,6917    ,129.4,129.5,129.1
XS GIS Cut Line= 2
2173752.79398855668520.8032988482173933.89005345668488.222932032
#Sta/Elev= 30
       0 1816.54     7.5  1816.6    11.6 1816.24    12.9  1815.8    15.6  1815.1
    19.7 1814.28    23.8 1813.88    27.8 1813.23    31.9 1812.78    40.5 1812.41
    48.1 1811.96    50.8 1811.95    64.1 1811.49      68 1811.78    71.5  1811.9
    76.6 1812.03    80.7 1811.99    84.7 1811.79    88.1 1811.17    92.8 1810.64
    95.6 1811.17     101 1812.47   113.2 1812.39   125.4 1813.26   137.6 1813.62
   147.3 1814.14   164.5 1815.42     166 1815.58   170.1 1816.29     184 1819.55
#Mann= 5, -1 ,  0
       0     0.1       0      10    0.05       0    88.1   0.045       0
    95.6    0.05       0     110     0.1       0
Bank Sta=88.1,95.6
XS Rating Curve= 0 ,0
Exp/Cntr(USF)=0,0
Exp/Cntr=0.3,0.1

Type RM Length L Ch R = 1 ,6788    ,354.5,353.9,351.2
XS GIS Cut Line= 3
2173732.28765368668657.895986039 2173996.5881785668598.919835873
2174044.64281937668583.629722867
#Sta/Elev= 30
       0 1815.12    16.3 1815.22    24.5 1816.46    28.6 1816.82    36.8 1817.13
    40.9 1817.06      45 1816.76    77.8 1813.46      90 1812.67     131  1812.5
   143.3 1811.94   151.5 1811.74   155.6 1811.37   157.51811.022   159.7 1810.62
   163.8 1810.28   167.7 1811.08     172  1811.8   174.7 1811.93   208.9 1812.94
     213 1813.31   217.1    1814   233.5 1817.31   248.5 1820.91   255.2 1822.77
   265.2 1825.85     283 1831.65   287.2 1832.84   308.1 1838.01   321.2 1840.48
#Mann= 4, -1 ,  0
       0     0.1       0   157.5   0.045       0   167.7     0.1       0
     230    0.05       0
Bank Sta=157.5,167.7
XS Rating Curve= 0 ,0
Exp/Cntr(USF)=0,0
Exp/Cntr=0.3,0.1

Type RM Length L Ch R = 1 ,6434    ,243.3,239.7,236.8
XS GIS Cut Line= 4
 2173928.0897906668988.8686546082173996.89529913668951.735523022
2174189.11386264668878.5614107792174234.98420165668834.875373619
#Sta/Elev= 30
       0 1814.01     8.7 1813.26    58.3 1813.29      86 1812.59   103.1 1811.89
   126.1 1811.64   129.2  1811.5   137.3 1809.86   141.6 1809.47   144.7 1809.87
   150.9 1811.11     154 1811.31   167.3 1810.73   184.4 1810.85   206.7 1810.43
   231.5 1811.03   244.3 1810.63   248.6 1810.85   252.9 1811.49   265.7 1815.82
     270 1816.92   274.9 1817.37   278.6 1818.13   291.7 1821.42     304  1824.9
   315.7 1829.33   326.8 1832.26   335.1 1834.97   340.8 1837.35   347.2 1840.44
#Mann= 6, -1 ,  0
       0     0.1       0      30    0.05       0      70     0.1       0
   137.3   0.045       0   144.7    0.05       0  248.19     0.1       0
#XS Ineff= 2 , 0
          124.42 1815.22
Permanent Ineff=
       F       F
Bank Sta=137.3,144.7
XS Rating Curve= 0 ,0
Exp/Cntr(USF)=0,0
Exp/Cntr=0.3,0.1

Type RM Length L Ch R = 1 ,6194    ,363.2,366.8,362.5
XS GIS Cut Line= 4
2174051.95234589669230.7063708832174132.85241471669172.727988232
 2174283.8658765669035.1978712462174343.19259363668967.781147233
#Sta/Elev= 30
       0 1820.58      15 1817.63    27.1  1816.2    38.5    1814    47.1 1813.32
    54.4 1812.21    71.3 1811.67      79 1811.99    93.8 1811.54   122.6 1811.35
   135.5 1810.21   142.31808.869   146.9  1808.4   149.7 1808.87   152.7 1809.75
   158.2 1810.44     229 1809.44   241.4 1809.77     246 1810.32   254.5 1813.02
   271.1 1816.82   282.6 1818.91   306.5 1824.86   338.4 1835.37   346.6 1837.75
   352.7 1839.09     365 1841.03   370.6 1842.34     383 1844.23   393.6 1846.94
#Mann= 6, -1 ,  0
       0    0.05       0      10     0.1       0  129.53    0.05       0
   142.3   0.045       0   149.7    0.05       0  259.53     0.1       0
Bank Sta=142.3,149.7
XS Rating Curve= 0 ,0
Exp/Cntr(USF)=0,0
Exp/Cntr=0.3,0.1

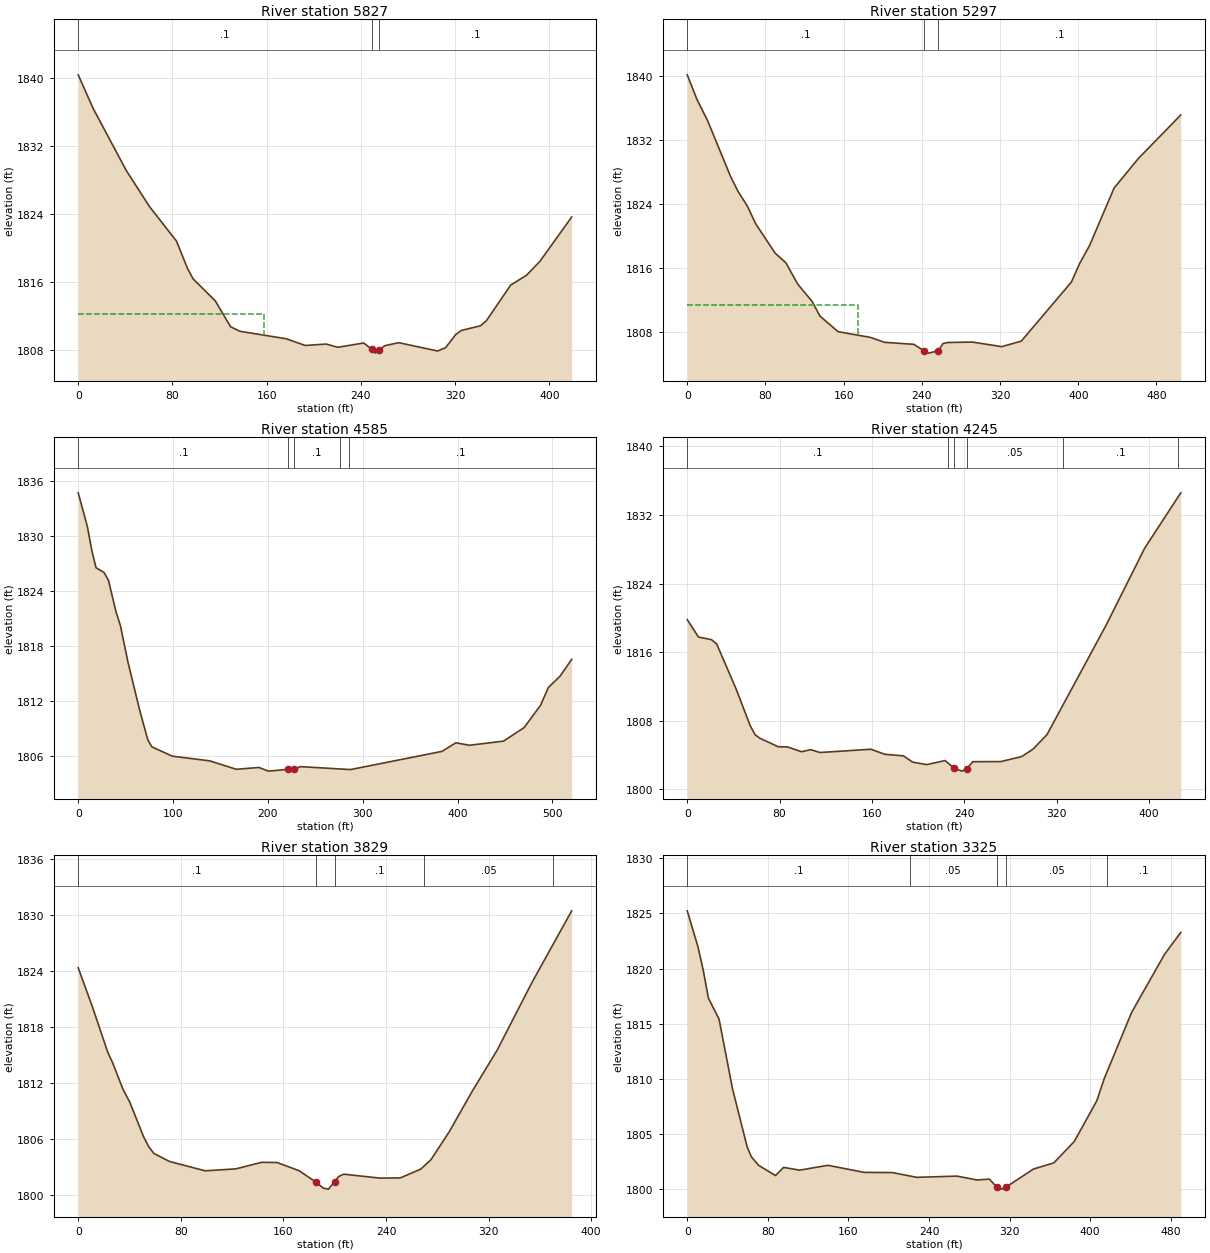
Type RM Length L Ch R = 1 ,5827    ,510.6,530.4,518.2
XS GIS Cut Line= 4
2174181.06337754669519.9031663672174262.27353632 669432.32358337
2174407.17793728669234.8714326142174450.96772878669202.228133497
#Sta/Elev= 30
       0 1840.41    12.6 1836.47    40.9 1829.12    60.7 1824.86    83.4 1820.84
    92.8 1817.62    97.5 1816.39   116.4 1813.79   129.4 1810.74   137.4 1810.21
   176.7 1809.33   192.8 1808.54   210.5 1808.71   220.3 1808.33   242.4 1808.83
   249.51808.071   252.3 1807.64   255.7 1808.05   260.4 1808.52   272.2 1808.87
   305.2 1807.89     312 1808.29   320.5 1809.83   325.5 1810.32   341.6 1810.86
   346.6 1811.46   367.2 1815.65   380.6 1816.81     392 1818.45     419 1823.67
#Mann= 3, -1 ,  0
       0     0.1       0   249.5   0.045       0   255.7     0.1       0
#XS Ineff= 2 , 0
           157.4 1812.26
Permanent Ineff=
       F       F
Bank Sta=249.5,255.7
XS Rating Curve= 0 ,0
Exp/Cntr(USF)=0,0
Exp/Cntr=0.3,0.1

Type RM Length L Ch R = 1 ,5297    ,686.8,711.6,689.4
XS GIS Cut Line= 3
2174394.58914148669717.6120748322174747.85277531669453.338516703
2174799.08948556669415.585151256
#Sta/Elev= 30
       0 1840.17      10 1837.08    20.8 1834.45    44.3 1827.47    51.9 1825.62
    61.5 1823.76      70 1821.56      90 1817.88   100.9 1816.69   112.9 1814.04
   127.6 1811.88   135.8 1810.02   154.3 1808.08   187.2 1807.37   201.8 1806.75
   231.8  1806.5   242.41805.679   246.8  1805.4   256.7 1805.69   261.7  1806.6
   266.7 1806.73   291.7 1806.78   321.7 1806.21   341.7  1806.9   392.9 1814.27
   401.5 1816.62   411.6 1818.86   436.6 1826.02   461.4 1829.71   504.8 1835.15
#Mann= 3, -1 ,  0
       0     0.1       0   242.4   0.045       0   256.7     0.1       0
#XS Ineff= 2 , 0
          174.16 1811.37
Permanent Ineff=
       F       F
Bank Sta=242.4,256.7
XS Rating Curve= 0 ,0
Exp/Cntr(USF)=0,0
Exp/Cntr=0.3,0.1

Type RM Length L Ch R = 1 ,4585    ,331.4,340.2,333.5
XS GIS Cut Line= 4
2174698.31694166670075.5262981472174789.19156928670045.783970043
2175105.36088032669833.6089471722175148.09343169669823.412001552
#Sta/Elev= 30
       0 1834.69     9.7 1830.99    14.6 1828.28    18.8 1826.52    27.2 1826.01
    31.9 1825.15    39.8 1821.74    44.6 1820.17    52.5 1816.21    65.1 1810.87
    73.5 1807.72    77.7    1807    99.2 1805.98   138.6 1805.47   166.7 1804.55
   190.5 1804.75   200.4 1804.35   221.5 1804.54   227.9 1804.54   234.1 1804.84
   287.1 1804.52   383.4  1806.5   398.2 1807.44   412.5 1807.17   448.4 1807.62
   470.1 1809.09   487.5 1811.54   495.7 1813.47   508.1 1814.71   520.3 1816.54
#Mann= 5, -1 ,  0
       0     0.1       0   221.5   0.045       0   227.9     0.1       0
  275.62    0.05       0  285.62     0.1       0
Bank Sta=221.5,227.9
XS Rating Curve= 0 ,0
Exp/Cntr(USF)=0,0
Exp/Cntr=0.3,0.1

Type RM Length L Ch R = 1 ,4245    ,410.2,416.5,406.8
XS GIS Cut Line= 4
 2174816.3171932670253.5789076862174869.28186297670235.685190744
2175177.59360431670208.5770009442175238.90505481670198.432327074
#Sta/Elev= 30
       0 1819.79     9.7 1817.77      21 1817.46    25.5 1816.96    42.1 1811.79
    54.7 1807.39    58.8 1806.38    62.8 1805.98    78.9 1804.98    86.9 1804.96
      99  1804.4     107 1804.64     115 1804.31   159.2 1804.69   171.2  1804.1
   187.3 1803.92   195.3 1803.19   207.4  1802.9   223.4 1803.37   231.5 1802.46
   238.1 1802.14   242.21802.443   247.5 1803.24   271.6 1803.25   289.7 1803.83
   299.7 1804.71   311.7 1806.39   363.5 1819.29   396.4 1828.13   427.6 1834.57
#Mann= 6, -1 ,  0
       0     0.1       0  225.91    0.05       0   231.5   0.045       0
   242.2    0.05       0  325.91     0.1       0  425.41    0.05       0
Bank Sta=231.5,242.2
XS Rating Curve= 0 ,0
Exp/Cntr(USF)=0,0
Exp/Cntr=0.3,0.1

Type RM Length L Ch R = 1 ,3829    ,482.4,503.4,488.9
XS GIS Cut Line= 3
2174869.19494637670538.8184077972175199.02452693670548.647766158
2175253.63207338670553.016369874
#Sta/Elev= 30
       0 1824.34      11 1820.19      23 1815.32      27 1814.12      35 1811.31
    40.2 1809.96      51 1806.25      55 1805.19      59 1804.47    71.2 1803.61
      99 1802.61     123 1802.82     143 1803.52     155  1803.5   172.3 1802.62
   185.21801.416   191.1 1800.76   195.1 1800.65   199.9 1801.45   203.1    1802
   207.1 1802.25   235.1 1801.83   251.1 1801.85   267.1 1802.79   275.1 1803.81
   289.4 1806.81   307.1  1811.1   326.5 1815.48   353.8 1822.77   384.8 1830.44
#Mann= 5, -1 ,  0
       0     0.1       0   185.2   0.045       0   199.9     0.1       0
     270    0.05       0  369.98     0.1       0
Bank Sta=185.2,199.9
XS Rating Curve= 0 ,0
Exp/Cntr(USF)=0,0
Exp/Cntr=0.3,0.1

Type RM Length L Ch R = 1 ,3325    ,223.1,213.5,198.8
XS GIS Cut Line= 4
2174835.80741386670793.1256680082174875.61631523670824.972789098
2175230.71171538670842.4887056972175292.01742347670785.960065763
#Sta/Elev= 30
       0 1825.24    10.7 1821.96    15.8 1819.89      21 1817.33    31.6 1815.41
    44.9 1809.12    59.5 1803.82    63.6 1802.94    70.8 1802.16    87.6 1801.23
    95.6 1801.97   111.6 1801.72   139.6 1802.16   175.7 1801.52   203.7  1801.5
   227.8 1801.07   267.8 1801.18   287.8 1800.83   299.9 1800.91     3071800.209
   311.9    1800   316.61800.194   343.9 1801.83   363.9 1802.38   384.2 1804.32
   406.5    1808   413.9 1810.01   441.1 1816.02   473.8 1821.29   489.9 1823.28
#Mann= 5, -1 ,  0
       0     0.1       0  220.98    0.05       0     307   0.045       0
   316.6    0.05       0  416.51     0.1       0
Bank Sta=307,316.6
XS Rating Curve= 0 ,0
Exp/Cntr(USF)=0,0
Exp/Cntr=0.3,0.1

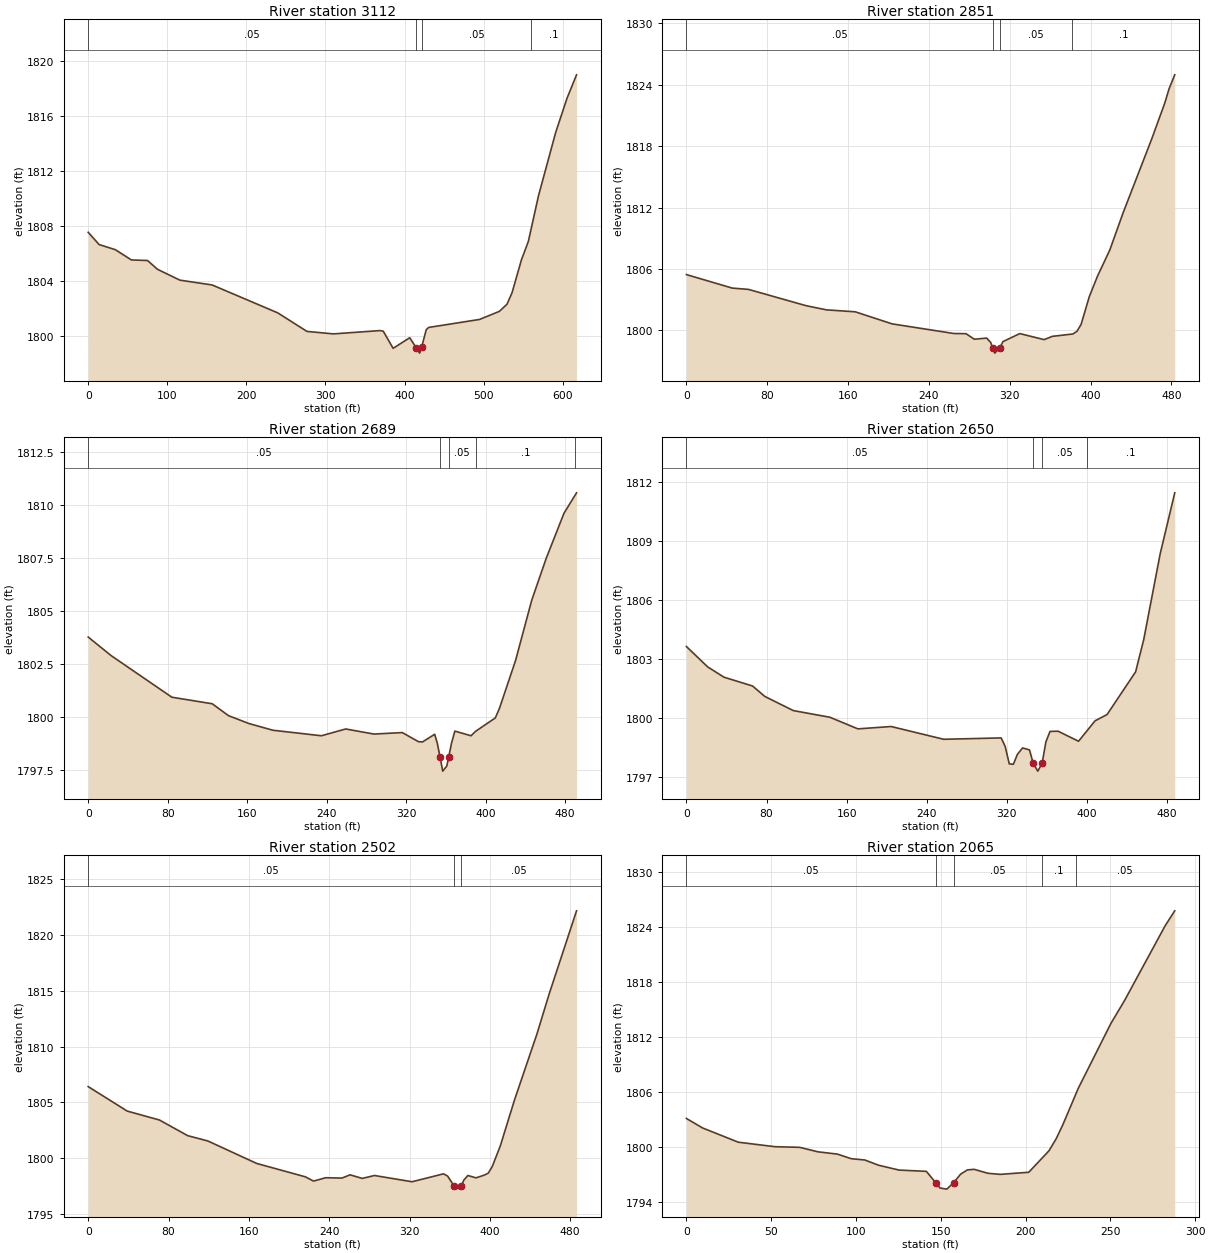
Type RM Length L Ch R = 1 ,3112    ,260.8,261.1,258
XS GIS Cut Line= 4
2175078.46402626671378.7314076442175121.91035951671164.496040227
2175217.98991197670857.5145766432175281.83542798670814.305995105
#Sta/Elev= 30
       0 1807.56    13.8 1806.67    34.2  1806.3    54.6 1805.55      75 1805.51
    87.6 1804.87   115.9 1804.08   156.7 1803.73   239.6  1801.7   276.6 1800.35
   310.1 1800.17   368.8 1800.41     373 1800.37   385.5 1799.12   406.5 1799.89
   414.6 1799.17   419.1 1798.77   421.5 1799.19   427.4 1800.48   430.5 1800.64
   494.7 1801.22   519.9 1801.81   529.5 1802.33   535.9 1803.17   547.7 1805.55
   556.5  1806.9   569.4 1810.24     591 1814.82   605.4 1817.32   617.4 1819.02
#Mann= 4, -1 ,  0
       0    0.05       0   414.6   0.045       0   421.5    0.05       0
  560.26     0.1       0
Bank Sta=414.6,421.5
XS Rating Curve= 0 ,0
Exp/Cntr(USF)=0,0
Exp/Cntr=0.3,0.1

Type RM Length L Ch R = 1 ,2851    ,158.6,162,159.2
XS GIS Cut Line= 4
2175330.29701706671393.8080994222175359.51876063671224.330757752
2175404.41829883 670977.990048212175422.62081431670919.741998664
#Sta/Elev= 30
       0 1805.45    45.3 1804.13    61.5    1804   118.4 1802.41   138.6    1802
   167.1 1801.81   203.6 1800.63   264.7 1799.69   276.8 1799.67     285 1799.13
   297.2 1799.24   301.2 1798.81   303.11798.307   305.3 1797.77  310.19  1798.3
   313.4  1798.9     330 1799.68   354.1 1799.09   362.2 1799.41   382.5 1799.64
   386.6  1799.9   390.7 1800.58   398.8 1803.29   406.9 1805.29   419.1 1807.85
   432.4 1811.52   460.6 1818.71   473.5 1822.21   477.7 1823.59   483.4 1824.98
#Mann= 4, -1 ,  0
       0    0.05       0   303.1   0.045       0  310.19    0.05       0
  381.98     0.1       0
Bank Sta=303.1,310.19
XS Rating Curve= 0 ,0
Exp/Cntr(USF)=0,0
Exp/Cntr=0.3,0.1

Type RM Length L Ch R = 1 ,2689    ,38.5,38.3,37.9
XS GIS Cut Line= 2
2175452.51787035671403.9507678062175543.47450536670920.801934619
#Sta/Elev= 30
       0 1803.78    23.2  1802.9    84.2 1800.94   124.9 1800.63   141.2 1800.07
   161.6  1799.7     186 1799.38   234.8 1799.12   259.2 1799.44   287.7  1799.2
   316.2 1799.27   332.5 1798.84   336.6 1798.83   348.8 1799.19   351.5 1798.76
   354.21798.112   356.9 1797.45     361 1797.69   362.91798.119   365.7 1798.76
   369.1 1799.34   385.4 1799.12     390 1799.33   409.8 1799.96   413.9  1800.4
   430.2 1802.67   446.5 1805.52   461.1  1807.5     479 1809.63   491.6 1810.59
#Mann= 5, -1 ,  0
       0    0.05       0   354.2   0.045       0   362.9    0.05       0
     390     0.1       0     490    0.05       0
Bank Sta=354.2,362.9
XS Rating Curve= 0 ,0
Exp/Cntr(USF)=0,0
Exp/Cntr=0.3,0.1

Type RM Length L Ch R = 1 ,2650    ,147.3,148.7,147.8
XS GIS Cut Line= 2
2175489.16544594 671410.141015862175579.10076919 670930.67984727
#Sta/Elev= 30
       0 1803.63    21.3 1802.59    37.5 1802.07    66.1 1801.62    78.3 1801.09
   106.8 1800.37   143.4 1800.03   171.3 1799.44   204.5 1799.56     257 1798.91
   314.4 1798.98   318.4 1798.55   322.5 1797.66   326.6 1797.64   330.6 1798.14
   335.8 1798.47   342.7 1798.37  346.41 1797.69     351 1797.29   355.31797.689
   359.1 1798.78   363.2 1799.31   371.3 1799.32   391.7 1798.81   408.2 1799.85
   420.2 1800.17   448.7 1802.34   456.8 1803.98   473.3 1808.36   487.8 1811.45
#Mann= 4, -1 ,  0
       0    0.05       0  346.41   0.045       0   355.3    0.05       0
     400     0.1       0
Bank Sta=346.41,355.3
XS Rating Curve= 0 ,0
Exp/Cntr(USF)=0,0
Exp/Cntr=0.3,0.1

Type RM Length L Ch R = 1 ,2502    ,434.6,436.8,431.2
XS GIS Cut Line= 3
2175651.80191994671439.9801147182175648.16141684671352.608040398
2175707.62296742670958.220204925
#Sta/Elev= 30
       0 1806.41    38.8 1804.22    70.9 1803.42      99 1802.02   119.2 1801.54
   167.8 1799.53   216.3 1798.33   224.4 1797.95   236.5 1798.25   252.7 1798.22
   260.8 1798.51   272.9 1798.19   285.1 1798.45   322.5 1797.89   353.9  1798.6
   357.9  1798.4   364.11797.548     370 1797.23   371.7 1797.55   374.1 1798.04
   378.1 1798.45   386.2 1798.24   394.3 1798.48   398.4 1798.66   402.4 1799.26
   410.4  1801.1   424.4 1805.18   446.9 1811.13     459 1814.69   486.3 1822.15
#Mann= 3, -1 ,  0
       0    0.05       0   364.1   0.045       0   371.7    0.05       0
Bank Sta=364.1,371.7
XS Rating Curve= 0 ,0
Exp/Cntr(USF)=0,0
Exp/Cntr=0.3,0.1

Type RM Length L Ch R = 1 ,2065    ,240.2,239.9,237.4
XS GIS Cut Line= 4
2176060.90794538671246.3060780752176036.22642653671170.669165487
2176017.91433191671020.1915183392176012.34108572670963.662878405
#Sta/Elev= 30
       0  1803.1     9.6 1802.06    30.6 1800.51    52.2 1800.02    66.8 1799.95
    77.6 1799.46    89.1 1799.21    97.2 1798.71   105.2 1798.57   113.3    1798
   125.4 1797.47   141.5 1797.33     1471796.099   149.6 1795.51   153.6 1795.39
   157.6  1796.1   161.7 1797.02   165.7 1797.49   169.7 1797.55   177.8 1797.12
   185.1    1797   201.9 1797.23   213.9 1799.59   218.1  1800.9   222.1 1802.46
   231.1 1806.39   250.4 1813.49   258.3 1815.94   282.4 1824.15     288 1825.76
#Mann= 5, -1 ,  0
       0    0.05       0     147   0.045       0   157.6    0.05       0
  209.56     0.1       0  229.56    0.05       0
Bank Sta=147,157.6
XS Rating Curve= 0 ,0
Exp/Cntr(USF)=0,0
Exp/Cntr=0.3,0.1

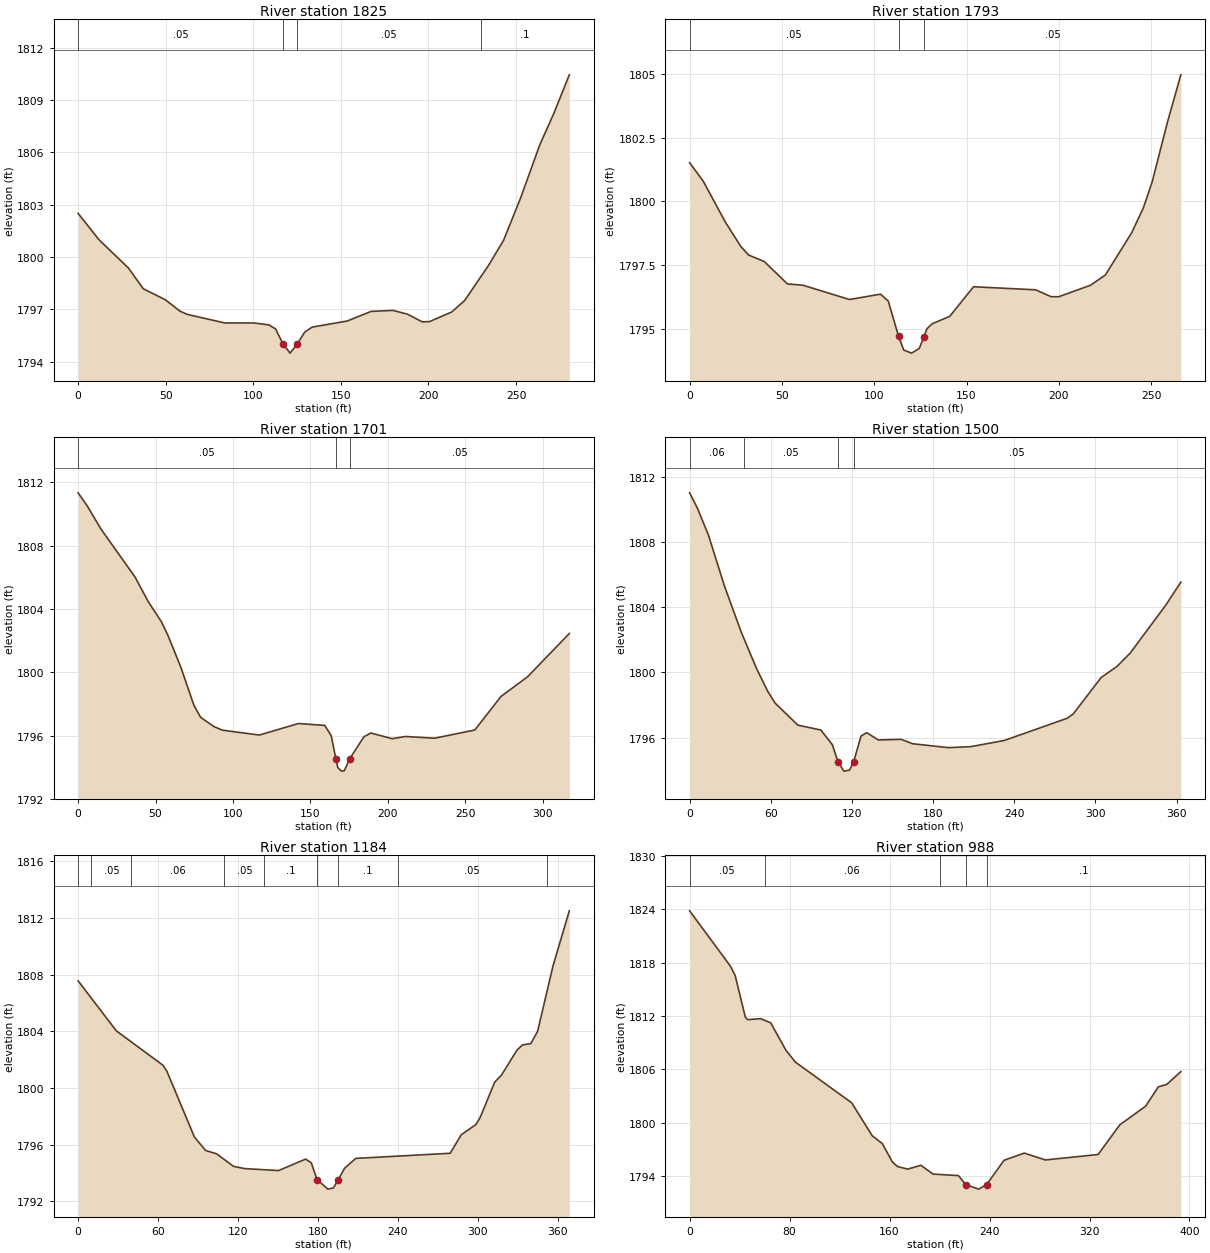
Type RM Length L Ch R = 1 ,1825    ,31.6,31.7,32.7
XS GIS Cut Line= 2
2176285.26874031671200.6479110772176201.16678332670933.193240398
#Sta/Elev= 30
       0  1802.5      12 1800.98    28.8 1799.36    37.2 1798.18    49.8 1797.55
    58.1  1796.9    62.3 1796.71    83.7 1796.22   100.1 1796.22   108.9 1796.11
   112.7 1795.88   116.9 1795.03     121 1794.49   125.2 1795.03   129.4  1795.7
   133.6 1795.98   153.6 1796.33   167.2 1796.88   179.7 1796.94   188.1 1796.72
   196.5 1796.28   200.7  1796.3   213.3 1796.85   220.6  1797.5   234.3 1799.52
   242.9 1800.96   252.5 1803.36   263.6 1806.44   271.6 1808.24   280.4 1810.44
#Mann= 4, -1 ,  0
       0    0.05       0   116.9   0.045       0   125.2    0.05       0
     230     0.1       0
Bank Sta=116.9,125.2
XS Rating Curve= 0 ,0
Exp/Cntr(USF)=0,0
Exp/Cntr=0.3,0.1

Type RM Length L Ch R = 1 ,1793    ,92.2,92.5,90.4
XS GIS Cut Line= 2
2176315.03074611671187.5995548932176233.54065114670934.248939113
#Sta/Elev= 30
       0 1801.52     7.4 1800.79    19.3  1799.2    27.8 1798.23      32  1797.9
    40.4 1797.65      53 1796.77    61.4 1796.72    86.6 1796.16   103.4 1796.37
   107.6  1796.1   113.21794.714     116 1794.18   120.2 1794.06   124.4 1794.24
   126.9  1794.7   128.6 1795.02   131.4 1795.21   140.9  1795.5   153.8 1796.66
   187.4 1796.54   195.8 1796.27     200 1796.27   217.2 1796.72   225.2 1797.12
   239.5 1798.78   245.8 1799.75   250.5 1800.75   258.9 1803.12   266.1 1804.96
#Mann= 3, -1 ,  0
       0    0.05       0   113.2   0.045       0   126.9    0.05       0
Bank Sta=113.2,126.9
XS Rating Curve= 0 ,0
Exp/Cntr(USF)=0,0
Exp/Cntr=0.3,0.1

Type RM Length L Ch R = 1 ,1701    ,199,200.4,194.7
XS GIS Cut Line= 4
2176412.68903584671190.3911156622176396.20815068671155.996224885
2176320.25276688670928.1300734892176317.38652598670889.435821365
#Sta/Elev= 30
       0 1811.34     5.8 1810.53    14.7 1809.06    36.8 1806.01    45.3 1804.46
    53.8 1803.19      58 1802.33    66.4  1800.3    74.8  1797.9    79.1 1797.15
    87.8 1796.56    93.1 1796.34     117 1796.03   142.3 1796.76   159.2 1796.64
   163.4 1795.99   166.41794.533   167.6 1793.98     170 1793.75   171.8 1793.77
   175.4 1794.54   184.5 1795.92     189 1796.16   202.7  1795.8   211.2 1795.94
   230.1 1795.83   256.1 1796.35     273 1798.47   290.1 1799.71   317.1 1802.45
#Mann= 3, -1 ,  0
       0    0.05       0   166.4   0.045       0   175.4    0.05       0
Bank Sta=166.4,175.4
XS Rating Curve= 0 ,0
Exp/Cntr(USF)=0,0
Exp/Cntr=0.3,0.1

Type RM Length L Ch R = 1 ,1500    ,304.6,316.3,320
XS GIS Cut Line= 4
2176515.87370818671158.8624657832176507.99154571671110.136370516
2176419.85463809 670858.623731712176401.94063248670814.913558015
#Sta/Elev= 30
       0 1811.01     5.8 1810.06    13.9 1808.42    25.6 1805.33    38.2 1802.46
    49.4 1800.25    57.7 1798.85    63.1 1798.13      80 1796.77      97 1796.47
   105.5 1795.57   109.7 1794.52     114 1793.95   118.2 1794.01  121.22 1794.52
   126.7  1796.1   130.9 1796.31   139.4 1795.86   156.3  1795.9   164.8 1795.63
   191.2 1795.39   207.8 1795.45   232.6 1795.83   279.1 1797.19   283.5 1797.45
   304.2 1799.69   315.9 1800.37   325.6 1801.18     352 1804.13   363.1 1805.54
#Mann= 4, -1 ,  0
       0    0.06       0      40    0.05       0   109.7   0.045       0
  121.22    0.05       0
Bank Sta=109.7,121.22
XS Rating Curve= 0 ,0
Exp/Cntr(USF)=0,0
Exp/Cntr=0.3,0.1

Type RM Length L Ch R = 1 ,1184    ,196.9,196,194.4
XS GIS Cut Line= 4
2176710.77808924671152.413423762 2176695.0137643671105.120448944
2176775.26850945670834.9772443012176801.06467753670808.464515994
#Sta/Elev= 30
       0 1807.56    28.7 1804.03    63.6 1801.61    66.5 1801.21    87.3 1796.54
    95.7 1795.59     104 1795.35   116.6 1794.47   124.9 1794.31   150.5 1794.17
   170.8 1794.98     175 1794.72   179.4 1793.53   187.5 1792.86   191.7 1792.95
   195.21793.523     200 1794.33   208.4 1795.03   279.3 1795.39   287.6  1796.7
   298.5 1797.41   301.7  1797.9   312.7 1800.41   317.8 1800.91   329.4 1802.67
   333.6 1803.04   339.8 1803.13   344.9    1804   356.5 1808.63   368.7  1812.5
#Mann= 9, -1 ,  0
       0    0.06       0      10    0.05       0      40    0.06       0
  109.85    0.05       0  139.85     0.1       0   179.4   0.045       0
   195.2     0.1       0  239.85    0.05       0  351.66     0.1       0
Bank Sta=179.4,195.2
XS Rating Curve= 0 ,0
Exp/Cntr(USF)=0,0
Exp/Cntr=0.3,0.1

Type RM Length L Ch R = 1 ,988     ,62.6,62,61.8
XS GIS Cut Line= 3
2176874.36672151671273.1295887022176919.93213058671007.955817067
2176880.05497119670890.486428812
#Sta/Elev= 30
       0 1823.81    32.7 1817.58    36.5 1816.51    44.6 1811.85    46.5 1811.58
    56.8 1811.69    64.9 1811.22    77.1 1808.13    84.6 1806.81   129.7 1802.23
   146.1 1798.53   154.2 1797.65   162.3 1795.57   166.4 1795.07   174.5 1794.78
   185.1 1795.21   194.8 1794.22   215.1 1794.05     2211793.037   231.3 1792.53
   237.71793.048   251.6 1795.77   267.8 1796.58   284.7 1795.81   326.9 1796.42
   344.2 1799.75   364.9 1801.85   375.1 1804.03   381.8  1804.3   393.1 1805.74
#Mann= 5, -1 ,  0
       0    0.05       0      60    0.06       0     200     0.1       0
     221   0.045       0   237.7     0.1       0
Bank Sta=221,237.7
XS Rating Curve= 0 ,0
Exp/Cntr(USF)=0,0
Exp/Cntr=0.3,0.1