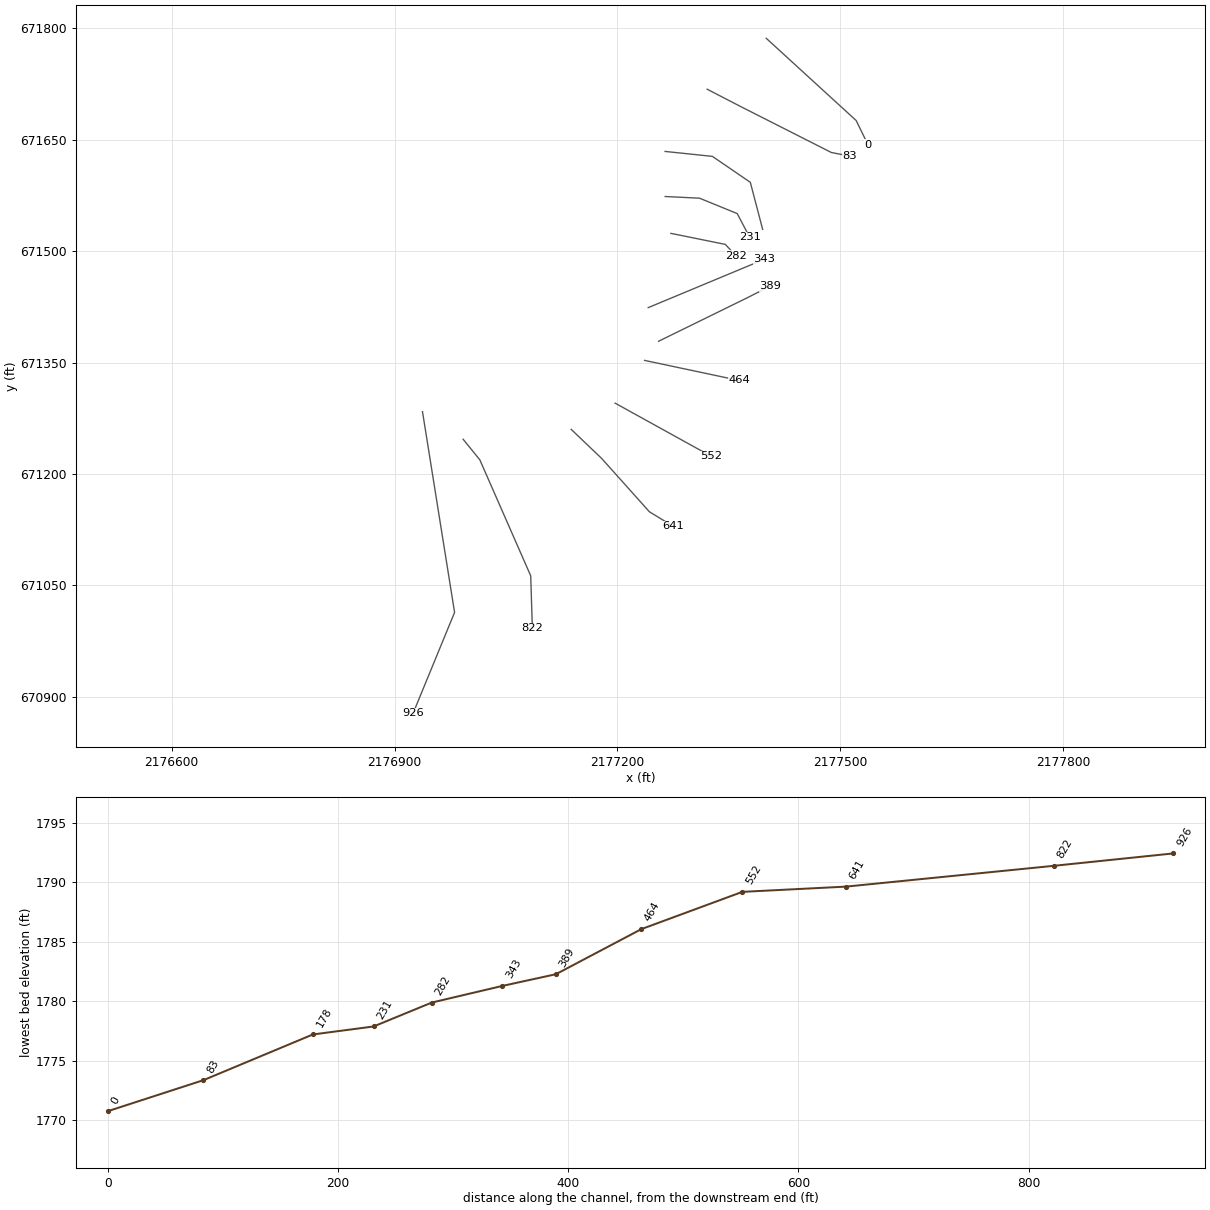
HEC-RAS study GRASSYCK.prj: GRASSYCK

--- GRASSYCK.g01 (geometry) --- (continued)

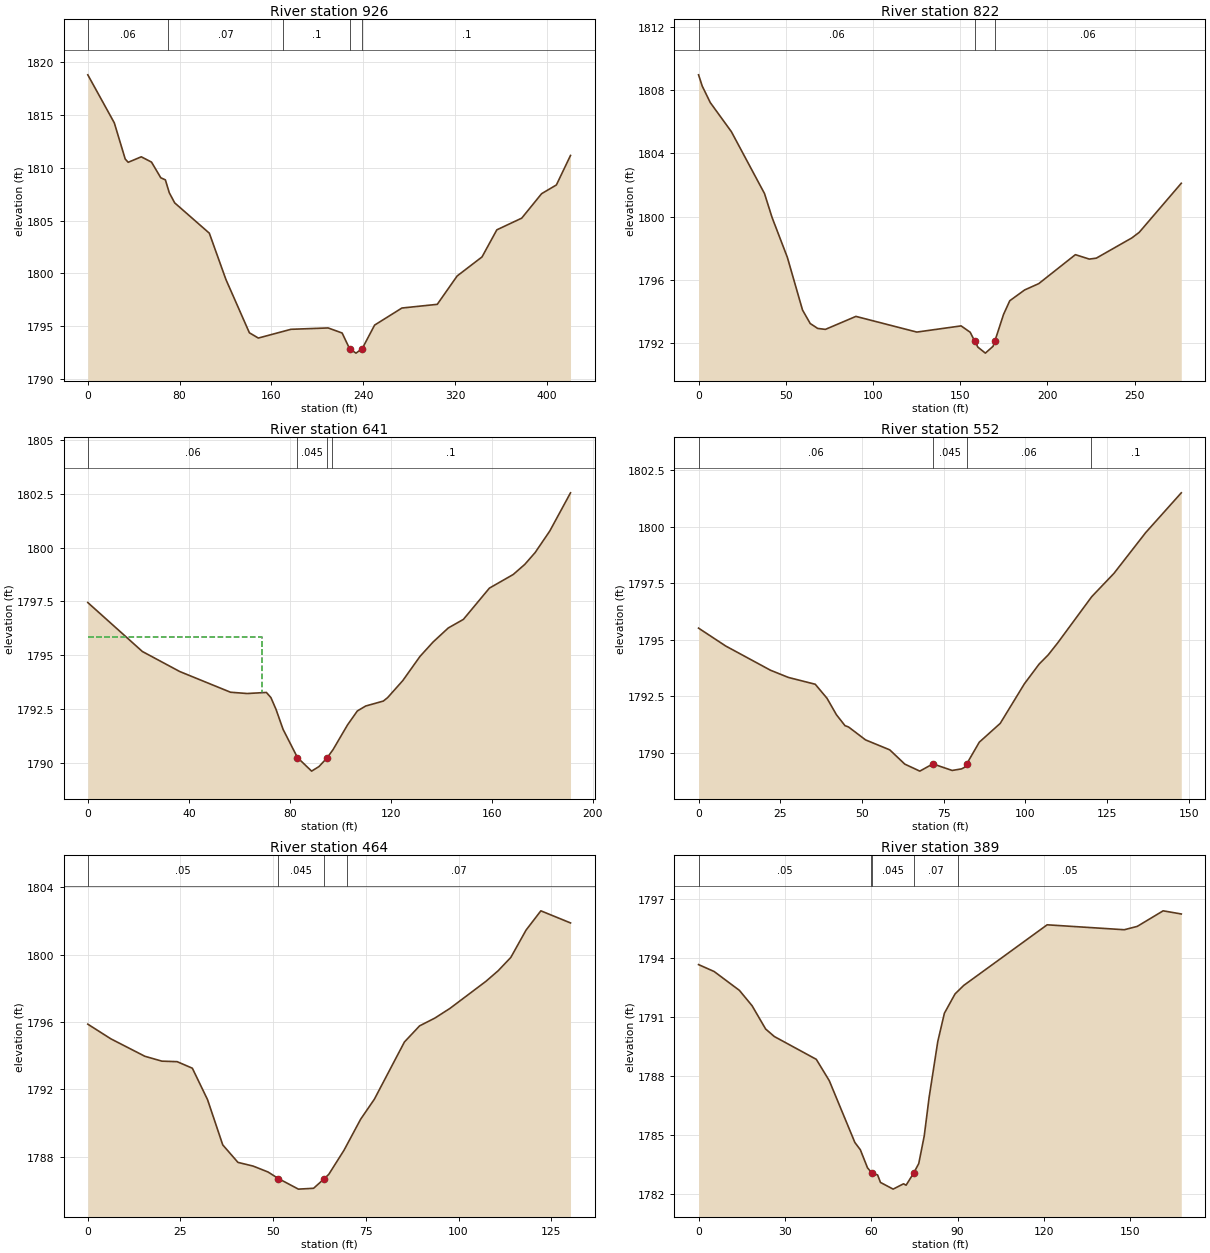
Type RM Length L Ch R = 1 ,926     ,101.8,103.7,106.9
XS GIS Cut Line= 3
2176937.63633541671283.9576098722176980.83974966671013.688298863
2176924.95056551670877.782966066
#Sta/Elev= 30
       0 1818.83    23.1 1814.27    32.6 1810.84    35.2 1810.53    46.6 1811.05
    55.5 1810.55    63.6 1809.06    67.6 1808.86      71 1807.64    75.7 1806.68
   105.9  1803.8   120.3 1799.42   140.8 1794.35   148.6 1793.85     177 1794.68
   209.4 1794.81   221.6 1794.33   228.2 1792.82   233.7 1792.42   239.11792.845
   249.9 1795.08   273.7  1796.7   304.5 1797.05   321.8 1799.74   343.5 1801.55
   356.4 1804.12   378.1 1805.23   395.4 1807.55   408.3 1808.38   420.6 1811.18
#Mann= 5, -1 ,  0
       0    0.06       0      70    0.07       0     170     0.1       0
   228.2   0.045       0   239.1     0.1       0
Bank Sta=228.2,239.1
XS Rating Curve= 0 ,0
Exp/Cntr(USF)=0,0
Exp/Cntr=0.3,0.1

Type RM Length L Ch R = 1 ,822     ,175.6,180.8,182.7
XS GIS Cut Line= 4
2176992.33570942671246.7897385092177014.84340236671219.048104473
2177083.33222862671062.9167971532177085.51318608670992.475760087
#Sta/Elev= 30
       0 1808.96     2.1 1808.25     6.7 1807.21    18.8 1805.37    37.8 1801.46
    42.1 1799.96    50.9 1797.43    59.6  1794.1      64 1793.25    68.3 1792.94
    72.7 1792.88    90.2  1793.7   125.1 1792.71   150.5  1793.1   155.7  1792.7
   158.21792.155   160.1 1791.76   164.4 1791.38   168.8 1791.81   169.91792.161
   174.8 1793.82   178.4 1794.69   186.9 1795.37     195 1795.77     216  1797.6
     224 1797.32     228 1797.38   248.4 1798.66   252.6 1799.01   276.7 1802.11
#Mann= 3, -1 ,  0
       0    0.06       0   158.2   0.045       0   169.9    0.06       0
Bank Sta=158.2,169.9
XS Rating Curve= 0 ,0
Exp/Cntr(USF)=0,0
Exp/Cntr=0.3,0.1

Type RM Length L Ch R = 1 ,641     ,87.6,90,94.1
XS GIS Cut Line= 4
2177137.81133912671260.0653731882177178.71309832671221.044154634
 2177243.1216157671149.1134746482177275.56094196671129.367797789
#Sta/Elev= 30
       0 1797.45    21.6 1795.18    36.4 1794.25    56.5 1793.29    63.1 1793.23
    70.7 1793.28    72.5 1793.04    74.5  1792.5    77.3 1791.57      83 1790.26
    88.6 1789.63    91.5 1789.84    94.7 1790.24    97.1 1790.63   102.8 1791.77
   106.7 1792.42     110 1792.65     117 1792.88   118.7 1793.04   124.7 1793.83
   131.5 1794.95   136.7 1795.62   142.7 1796.27   148.7 1796.67     159 1798.12
   168.4 1798.75     173 1799.22   177.1 1799.77   182.9 1800.77   191.1 1802.54
#Mann= 4, -1 ,  0
       0    0.06       0      83   0.045       0    94.7    0.06       0
   96.53     0.1       0
#XS Ineff= 2 , 0
           68.88 1795.85
Permanent Ineff=
       F       F
Bank Sta=83,94.7
XS Rating Curve= 0 ,0
Exp/Cntr(USF)=0,0
Exp/Cntr=0.3,0.1

Type RM Length L Ch R = 1 ,552     ,85.1,87.7,91.5
XS GIS Cut Line= 2
2177196.95394298671295.3598336712177326.24111289671223.899288848
#Sta/Elev= 28
       0 1795.51     8.3 1794.72      22 1793.65    27.5 1793.33    35.7 1793.03
    39.3 1792.41    42.2 1791.68    44.8  1791.2    45.9 1791.14    51.1 1790.57
    58.5 1790.13    63.1  1789.5    67.7 1789.19    71.7 1789.51    77.6 1789.22
    80.5 1789.29    81.4 1789.36      821789.498    85.9 1790.47    92.3  1791.3
    99.7 1793.05   104.2 1793.92     107 1794.33   109.9 1794.86   120.3  1796.9
   127.1 1797.93   136.8 1799.73   147.7 1801.49
#Mann= 4, -1 ,  0
       0    0.06       0    71.7   0.045       0      82    0.06       0
     120     0.1       0
Bank Sta=71.7,82
XS Rating Curve= 0 ,0
Exp/Cntr(USF)=0,0
Exp/Cntr=0.3,0.1

Type RM Length L Ch R = 1 ,464     ,66.8,74.3,82.5
XS GIS Cut Line= 3
2177236.59360221671352.915258909 2177322.1306212671334.778574701
  2177363.955352671325.879399097
#Sta/Elev= 29
       0 1795.87     6.2    1795    15.4 1793.96      20 1793.67    24.1 1793.64
    28.2 1793.25    32.3 1791.38    36.4 1788.69    40.5 1787.65    44.6 1787.43
    48.6 1787.08    51.41786.691    56.8 1786.06    60.9 1786.11    63.81786.684
      65 1786.94    69.1 1788.37    73.6 1790.22    77.3 1791.41    85.4 1794.81
    89.5 1795.77    93.6 1796.23    97.7 1796.81   107.4 1798.42   110.7 1799.05
   114.1 1799.84   118.2 1801.46   122.2 1802.61   130.2 1801.89
#Mann= 4, -1 ,  0
       0    0.05       0    51.4   0.045       0    63.8    0.05       0
      70    0.07       0
Bank Sta=51.4,63.8
XS Rating Curve= 0 ,0
Exp/Cntr(USF)=0,0
Exp/Cntr=0.3,0.1

Type RM Length L Ch R = 1 ,389     ,46.9,46.4,46
XS GIS Cut Line= 3
2177255.45377475671378.6851626842177375.01900826 671437.30695193
2177405.78093727671452.978123312
#Sta/Elev= 30
       0 1793.67     5.4 1793.32    14.2 1792.36    18.6 1791.58    23.3  1790.4
    26.3 1790.02    40.9 1788.86    45.4 1787.78    54.3 1784.64    56.2 1784.27
    58.7 1783.35    60.2 1783.09    62.2 1782.99    63.2 1782.61    67.6 1782.27
    71.2 1782.54    72.1 1782.47    74.81783.103    76.5 1783.57    78.4 1784.97
    80.1 1786.93    83.1 1789.76    85.4  1791.2    89.1 1792.18    92.1 1792.61
   121.1 1795.69   147.9 1795.44   152.4 1795.61   161.4  1796.4   167.7 1796.24
#Mann= 5, -1 ,  0
       0    0.05       0      60    0.07       0    60.2   0.045       0
    74.8    0.07       0      90    0.05       0
Bank Sta=60.2,74.8
XS Rating Curve= 0 ,0
Exp/Cntr(USF)=0,0
Exp/Cntr=0.3,0.1

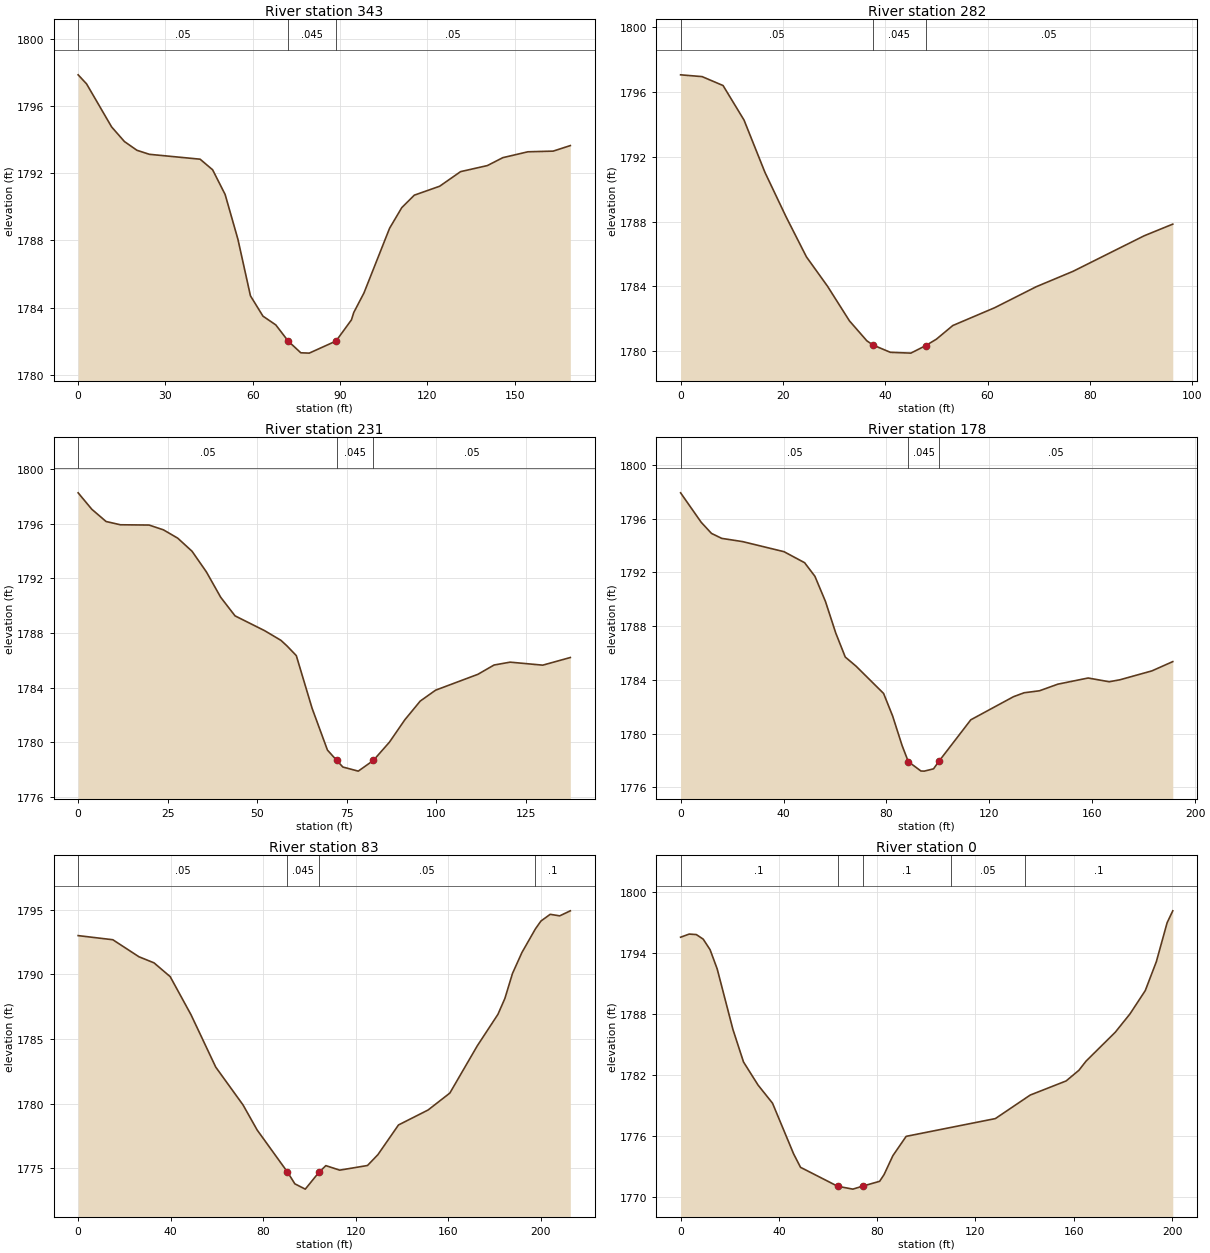
Type RM Length L Ch R = 1 ,343     ,67.9,61.4,53.7
XS GIS Cut Line= 2
2177241.52384463671423.957435567 2177397.6551447671488.963776116
#Sta/Elev= 30
       0 1797.85     2.9 1797.31    11.5 1794.75    15.9 1793.88    20.2 1793.36
    24.5 1793.12    41.9 1792.83    46.2  1792.2    50.5 1790.73    54.9 1788.06
    59.2  1784.7    63.5 1783.49    67.9 1782.97    72.2    1782    76.5 1781.31
    79.4 1781.29    88.6 1782.01    93.9 1783.27    94.7 1783.71    98.2 1784.87
     107 1788.72   111.2 1789.95   115.5 1790.69   124.2 1791.22   131.4 1792.09
   140.6 1792.45   145.9 1792.92   154.5 1793.27   163.2 1793.31   169.1 1793.64
#Mann= 3, -1 ,  0
       0    0.05       0    72.2   0.045       0    88.6    0.05       0
Bank Sta=72.2,88.6
XS Rating Curve= 0 ,0
Exp/Cntr(USF)=0,0
Exp/Cntr=0.3,0.1

Type RM Length L Ch R = 1 ,282     ,53.1,50.6,49.3
XS GIS Cut Line= 4
2177272.01994473671523.8772878122177288.94481061671520.492314636
2177345.21998966671509.068030168 2177360.0292473 671493.41252923
#Sta/Elev= 21
       0 1797.04     4.2 1796.93     8.3 1796.38    12.4 1794.25    16.5 1791.02
    20.6  1788.3    24.6 1785.82    28.7 1784.02      33 1781.88    36.4 1780.65
    37.6 1780.39      41 1779.94      45 1779.89    47.9 1780.35      50 1780.75
    53.2 1781.59    61.4 1782.69    69.5 1783.98    76.7 1784.93    90.6 1787.12
    96.2 1787.84
#Mann= 3, -1 ,  0
       0    0.05       0    37.6   0.045       0    47.9    0.05       0
Bank Sta=37.6,47.9
XS Rating Curve= 0 ,0
Exp/Cntr(USF)=0,0
Exp/Cntr=0.3,0.1

Type RM Length L Ch R = 1 ,231     ,55.5,52.7,50.6
XS GIS Cut Line= 4
2177264.39030115671573.510126755 2177310.5240146671571.266912273
2177361.29861224671550.5339515712177378.22347812671518.376706401
#Sta/Elev= 30
       0 1798.26     3.8 1797.06     7.8 1796.16    11.8 1795.92    19.8  1795.9
    23.8 1795.55    27.8 1794.94    31.8 1793.98    35.8 1792.47    39.8 1790.61
    43.8 1789.25    52.1 1788.16    56.6 1787.46    58.3 1787.05    60.9 1786.34
    65.3 1782.49    69.6 1779.42    72.21778.665    73.9 1778.18    78.2 1777.88
    82.4 1778.66    86.9    1780    91.2 1781.64    95.5 1783.01    99.8 1783.81
   111.6 1784.97   116.1 1785.65   120.6 1785.86   129.7 1785.64   137.4  1786.2
#Mann= 3, -1 ,  0
       0    0.05       0    72.2   0.045       0    82.4    0.05       0
Bank Sta=72.2,82.4
XS Rating Curve= 0 ,0
Exp/Cntr(USF)=0,0
Exp/Cntr=0.3,0.1

Type RM Length L Ch R = 1 ,178     ,89.1,95.1,93.9
XS GIS Cut Line= 4
  2177264.222392671634.1844314252177327.87200213671627.542091321
2177378.91009804671592.6479751442177395.52916378671529.323411722
#Sta/Elev= 30
       0 1797.92       8 1795.73      12  1794.9      16 1794.53    24.1 1794.29
    40.2 1793.54    48.2 1792.72    52.2 1791.71    56.3 1789.84    60.3 1787.49
      64  1785.7    68.2 1785.02    78.9 1782.99    82.4 1781.32    86.1 1779.11
    88.51777.918    93.4 1777.22    94.7 1777.21    98.3 1777.38   100.51777.967
   112.8 1781.03   129.4 1782.75   133.5 1783.04   139.5 1783.19   146.6 1783.68
   158.4 1784.14   166.6 1783.86   170.8 1784.01   183.2 1784.67   191.3 1785.36
#Mann= 3, -1 ,  0
       0    0.05       0    88.5   0.045       0   100.5    0.05       0
Bank Sta=88.5,100.5
XS Rating Curve= 0 ,0
Exp/Cntr(USF)=0,0
Exp/Cntr=0.3,0.1

Type RM Length L Ch R = 1 ,83      ,84,83.2,81.2
XS GIS Cut Line= 4
2177320.80199709671717.9594231732177366.98033722671694.074074829
 2177487.9994355671632.7683474132177512.68096212671627.991277745
#Sta/Elev= 30
       0 1793.01      15 1792.69    26.3 1791.37    32.8  1790.9    39.8 1789.83
    48.8 1786.88    59.5 1782.82    71.3 1779.89    77.4 1777.95    90.51774.694
    93.7 1773.78    98.2 1773.37   104.1 1774.67   107.1 1775.19   113.1 1774.84
   125.1  1775.2   129.6 1776.04   138.5 1778.34   151.3  1779.5   160.7 1780.81
   172.6 1784.48   181.5 1786.91   184.5 1788.14   187.8 1790.08   191.9 1791.71
   197.7 1793.53   200.1 1794.14   204.1 1794.66   208.2 1794.54   212.8 1794.93
#Mann= 4, -1 ,  0
       0    0.05       0    90.5   0.045       0   104.1    0.05       0
  197.65     0.1       0
Bank Sta=90.5,104.1
XS Rating Curve= 0 ,0
Exp/Cntr=0.3,0.1

Type RM Length L Ch R = 1 ,0       ,105.7,100.2,96.6
XS GIS Cut Line= 3
 2177400.4198249671786.4307550922177521.43892318671675.761974432
2177537.36248874671643.118665029
#Sta/Elev= 30
       0 1795.58     3.5 1795.89     6.4 1795.84     9.2 1795.39      12 1794.35
    14.9 1792.45    21.3 1786.49    25.6 1783.29    31.5 1781.02    37.4 1779.23
      46 1774.23    48.8 1772.91    63.91771.043    70.1 1770.76    74.3 1771.07
      81 1771.53    82.8 1772.19    86.4 1774.06    91.8 1775.96   128.1 1777.71
   142.3 1780.03   156.9 1781.42   162.1 1782.47     165 1783.37   176.9 1786.22
   182.9 1788.03   189.1 1790.32   193.6 1793.16     198 1797.01   200.3 1798.18
#Mann= 5, -1 ,  0
       0     0.1       0    63.9   0.045       0    74.3     0.1       0
     110    0.05       0     140     0.1       0
Bank Sta=63.9,74.3
XS Rating Curve= 0 ,0
Exp/Cntr=0.3,0.1
LCMann Table=0

Chan Stop Cuts=-1
Use User Specified Reach Order=0
Composite Channel Slope=5